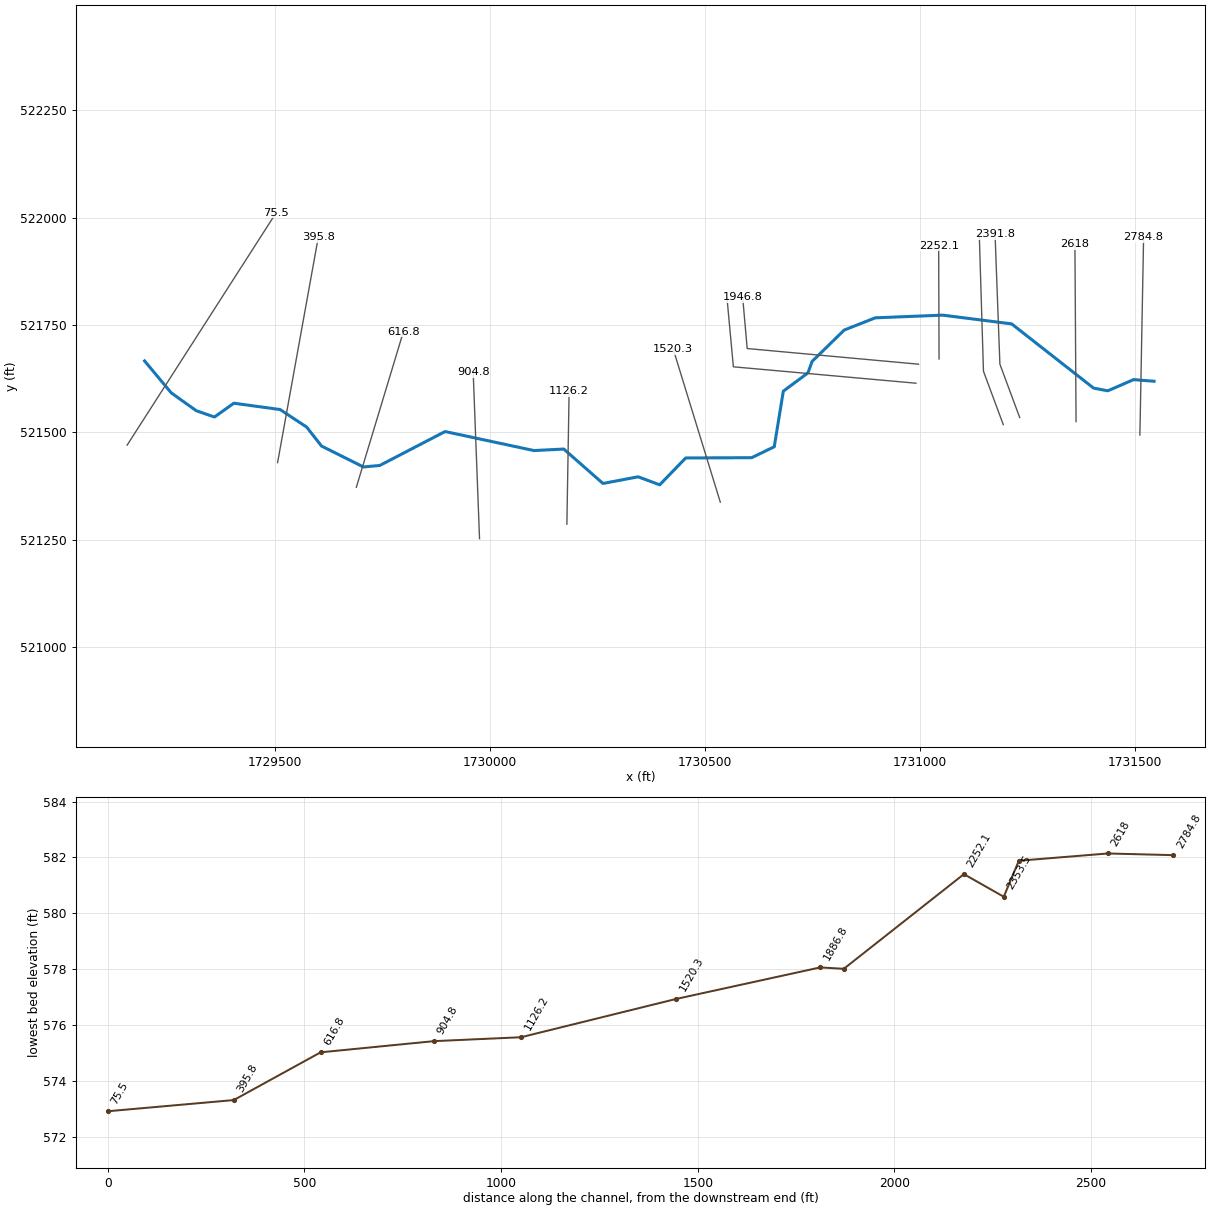
--- NP4.prj (project) ---

Proj Title=NP4
Current Plan=p01
Default Exp/Contr=0,0
English Units
Geom File=g01
Flow File=f01
Plan File=p01
BEGIN DESCRIPTION:
AMEC Environment & Infrastructure, 2013
Projection: NAD 1983 State Plane West Virginia South FIPS 4702 (US Feet)
Vertical Datum: NAVD 1988
END DESCRIPTION:
DSS Export Rating Curves= 0
DSS Export Rating Curve Sorted= 0
DSS Export Volume Flow Curves= 0
DXF OffsetX= 0
DXF OffsetY= 0
DXF ScaleX= 0
DXF ScaleY= 0

--- NP4.p01 (plan) ---

Plan Title=Floodplain
Program Version=4.00
Geom File=g01
Flow File=f01
K Sum by GR=0
Std Step Tol=0.01
Critical Tol=0.01
Num of Std Step Trials=20
Max Error Tol=0.3
Flow Tol Ratio=0.001
Split Flow NTrial=30
Split Flow Tol=0.02
Split Flow Ratio=0.02
Log Output Level=0
Friction Slope Method=1
Unsteady Friction Slope Method=2
Unsteady Bridges Friction Slope Method=1
Global Log Level=0
CheckData=False
Run HTab=0
Run UNet=0
Run PostProcess=0
UNET Theta=0
UNET Theta Warmup=0
UNET ZTol=0
UNET ZSATol=0
UNET MxIter=0
UNET MaxInSteps=0
UNET DtIC=0
UNET DtMin=0
UNET MaxCRTS=0
UNET WFStab=0
UNET SFStab=0
UNET WFX=0
UNET SFX=0
UNET DSS MLevel=0
UNET DZMax Abort=0
UNET Convert EG Bridges=0
UNET Use Existing IB Tables=0
UNET Froude Limit=0
UNET Froude Power=0
Write IC File=0
Echo Input=False
Echo Output=False
Write Detailed=0

--- NP4.f01 (steady flow) ---

Flow Title=USGS Regress. Eqn. (2010) - Western-Plateaus
Program Version=4.10
Number of Profiles= 1
Profile Names=P100yr
River Rch & RM=NP4,Main            ,2784.8
    1007
River Rch & RM=NP4,Main            ,75.5
    1045
Boundary for River Rch & Prof#=NP4,Main            , 1
Up Type= 0
Dn Type= 3
Dn Slope=0.00266
DSS Import GetInterval= 0
DSS Import GetPeak= 0
DSS Import FillOption= 0

--- NP4.g01 (geometry) ---

Geom Title=USGS 3m DEM
Program Version=4.10

River Reach=NP4             ,Main
Reach XY= 30
     1731544.883      521618.876       1731497.3      521622.694
     1731437.216      521596.642      1731404.22      521602.892
     1731213.623      521752.446     1731053.333      521772.844
     1730896.388      521766.594     1730824.166      521738.122
      1730749.49       521665.09     1730739.768      521638.354
       1730682.5      521595.761      1730661.43      521466.341
     1730608.888        521440.9     1730455.416      521440.205
        1730395.      521377.705     1730344.946      521396.357
     1730263.063      521380.882     1730171.822      521460.974
     1730102.378      521457.501     1729895.781      521501.772
     1729743.871      521422.779     1729705.955      521419.291
     1729608.454      521467.918     1729573.732      521512.189
       1729512.1      521552.987     1729404.461      521567.744
     1729359.322      521535.626     1729316.788      521550.383
     1729258.628       521592.05     1729196.779      521666.225

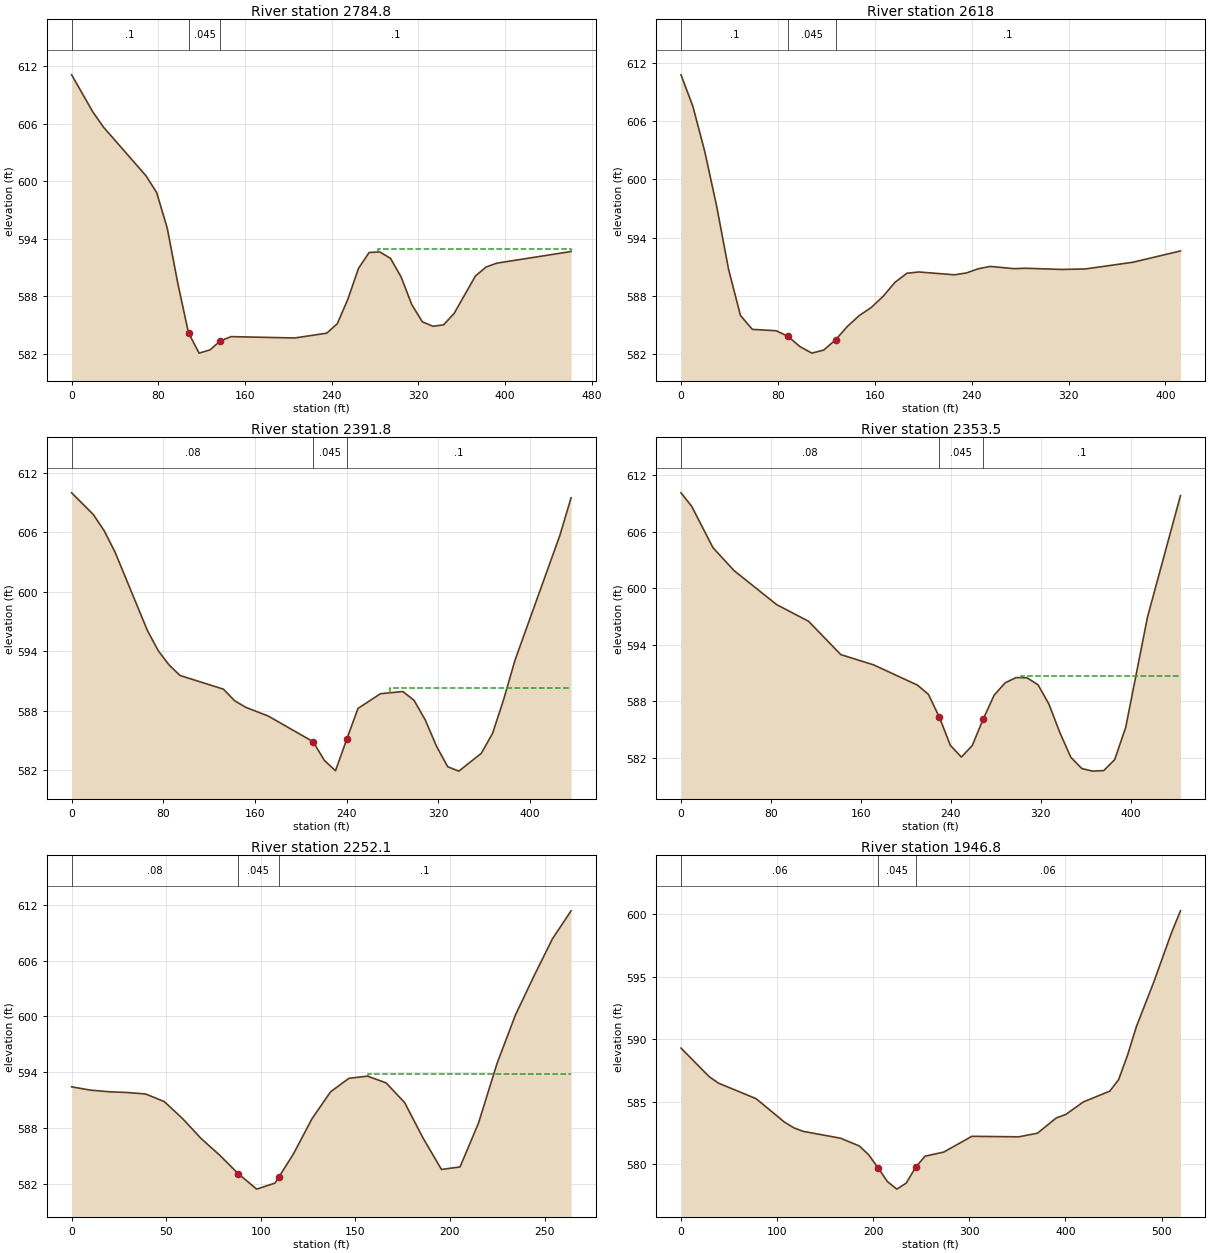
Type RM Length L Ch R = 1 ,2784.8  ,163.3,166.8,171.4
XS GIS Cut Line= 2
     1731511.894      521493.667     1731520.554      521954.729
#Sta/Elev= 30
       0  611.09    19.6  607.22    29.4  605.64    68.7  600.56    78.5  598.82
    88.3   595.1    98.1  589.31   107.9  584.19   117.7  582.08   127.6  582.41
   137.4  583.36   147.2   583.8     206  583.66   235.5  584.16   245.3  585.15
   255.1  587.72   264.9  590.93   274.7  592.57   284.5  592.63   294.4  591.96
   304.2  590.02     314  587.15   323.8  585.34   333.6  584.88   343.4  585.03
   353.2  586.23   372.8  590.12   382.6  591.05   392.5  591.46   461.1  592.67
#Mann= 3 , 0 , 0
       0      .1       0   107.9    .045       0   137.4      .1       0
#XS Ineff= 2 , 0
                           283.1          592.91
Permanent Ineff=
       F       F
Bank Sta=107.9,137.4
XS Rating Curve= 0 ,0
Exp/Cntr=0.3,0.1

Type RM Length L Ch R = 1 ,2618    ,227.7,226.3,221.9
XS GIS Cut Line= 2
     1731363.414      521524.918     1731360.789      521937.356
#Sta/Elev= 30
       0  610.74     9.8   607.5    19.6  602.87    29.5   597.2    39.3  590.74
    49.1  586.01    58.9  584.58    78.6  584.44    88.4  583.86    98.2  582.81
     108  582.14   117.8  582.45   127.7  583.52   137.5   584.9   147.3  586.01
   157.1  586.83   166.9  587.98   176.8  589.43   186.6  590.35   196.4  590.48
   225.9  590.19   235.7  590.38   245.5  590.81   255.3  591.05     275  590.82
   284.8  590.86   314.2  590.74   333.9  590.79   373.2  591.48   412.4  592.64
#Mann= 3 , 0 , 0
       0      .1       0    88.4    .045       0   127.7      .1       0
Bank Sta=88.4,127.7
XS Rating Curve= 0 ,0
Exp/Cntr=0.3,0.1

Type RM Length L Ch R = 1 ,2391.8  ,38.5,38.3,38.2
XS GIS Cut Line= 3
     1731232.302      521534.463     1731186.277      521658.626
     1731174.974      521961.659
#Sta/Elev= 30
       0  609.99    18.9   607.8    28.4  606.16    37.8  604.02    66.2  596.06
    75.7  594.02    85.1  592.59    94.6  591.54   132.4  590.16   142.2  588.99
     152  588.32   171.6  587.44   210.7  584.85   220.5  582.96   230.2  581.92
     240   585.1   249.8  588.21   269.4   589.7   288.9  589.92   298.7  589.04
   308.5  587.05   318.3   584.4   328.1  582.32   337.8  581.88   357.4  583.68
   367.2  585.69     377  589.16   386.8  593.09   425.9  605.68   435.7  609.49
#Mann= 3 , 0 , 0
       0     .08       0   210.7    .045       0     240      .1       0
#XS Ineff= 2 , 0
                          277.46          590.29
Permanent Ineff=
       F       F
Bank Sta=210.7,240
XS Rating Curve= 0 ,0
Exp/Cntr=0.3,0.1

Type RM Length L Ch R = 1 ,2353.5  ,102,101.3,100.8
XS GIS Cut Line= 3
     1731194.098      521517.963     1731148.073      521642.126
     1731138.506      521953.842
#Sta/Elev= 30
       0  610.14     9.5  608.71    28.4  604.32    47.3  601.87    85.1  598.27
   113.5   596.5   142.2  592.96   171.4  591.87   210.4  589.72   220.1  588.74
   229.9   586.3   239.6  583.33   249.4  582.08   259.1  583.31   268.9  586.14
   278.6  588.66   288.4  589.97   298.1  590.52   307.8   590.5   317.6  589.76
   327.3  587.71   337.1  584.66   346.8  582.06   356.6  580.86   366.3  580.59
   376.1  580.65   385.8  581.81   395.6  585.23     415  596.95   444.3  609.84
#Mann= 3 , 0 , 0
       0     .08       0   229.9    .045       0   268.9      .1       0
#XS Ineff= 2 , 0
                          302.82          590.66
Permanent Ineff=
       F       F
Bank Sta=229.9,268.9
XS Rating Curve= 0 ,0
Exp/Cntr=0.3,0.1

Type RM Length L Ch R = 1 ,2252.1  ,270.1,305.4,348.8
XS GIS Cut Line= 2
     1731044.745      521670.775     1731043.863      521934.735
#Sta/Elev= 30
       0  592.42     9.8  592.07    19.6  591.89    29.3  591.81    39.1  591.65
    48.9  590.84    58.7  588.99    68.4  586.86    78.2  585.07      88  583.08
    94.4  581.98    97.8   581.4   107.5  582.05   109.4  582.66   117.3  585.21
   127.1     589   136.9  591.89   146.6  593.34   156.4  593.57   166.2  592.85
     176  590.73   185.8  586.89   195.5  583.52   205.3  583.79   215.1  588.53
   224.9  594.96   234.6  600.16   244.4  604.36   254.2  608.38     264  611.38
#Mann= 3 , 0 , 0
       0     .08       0      88    .045       0   109.4      .1       0
#XS Ineff= 2 , 0
                          156.76          593.77
Permanent Ineff=
       F       F
Bank Sta=88,109.4
XS Rating Curve= 0 ,0
Exp/Cntr=0.3,0.1

Type RM Length L Ch R = 1 ,1946.8  ,57.9,59.9,55.1
XS GIS Cut Line= 3
     1730996.989      521658.617     1730598.442      521695.065
     1730588.017       521814.02
#Sta/Elev= 30
       0  589.28    29.3     587      39  586.48    78.1  585.24   107.4  583.38
   117.1  582.92   126.9  582.63   165.9  582.08   185.5  581.46   195.2  580.76
     205  579.71   214.8  578.61   224.5  578.01   234.3  578.49     244  579.74
   253.8  580.64   273.3  580.97   302.6  582.23   351.4  582.19   370.9  582.48
   390.4   583.7   400.2  583.97   418.6  584.98   446.1  585.84   455.3  586.76
   464.5   588.7   473.7  590.98   492.1  594.61   510.4  598.52   519.6  600.25
#Mann= 3 , 0 , 0
       0     .06       0     205    .045       0     244     .06       0
Bank Sta=205,244
XS Rating Curve= 0 ,0
Exp/Cntr=0.3,0.1

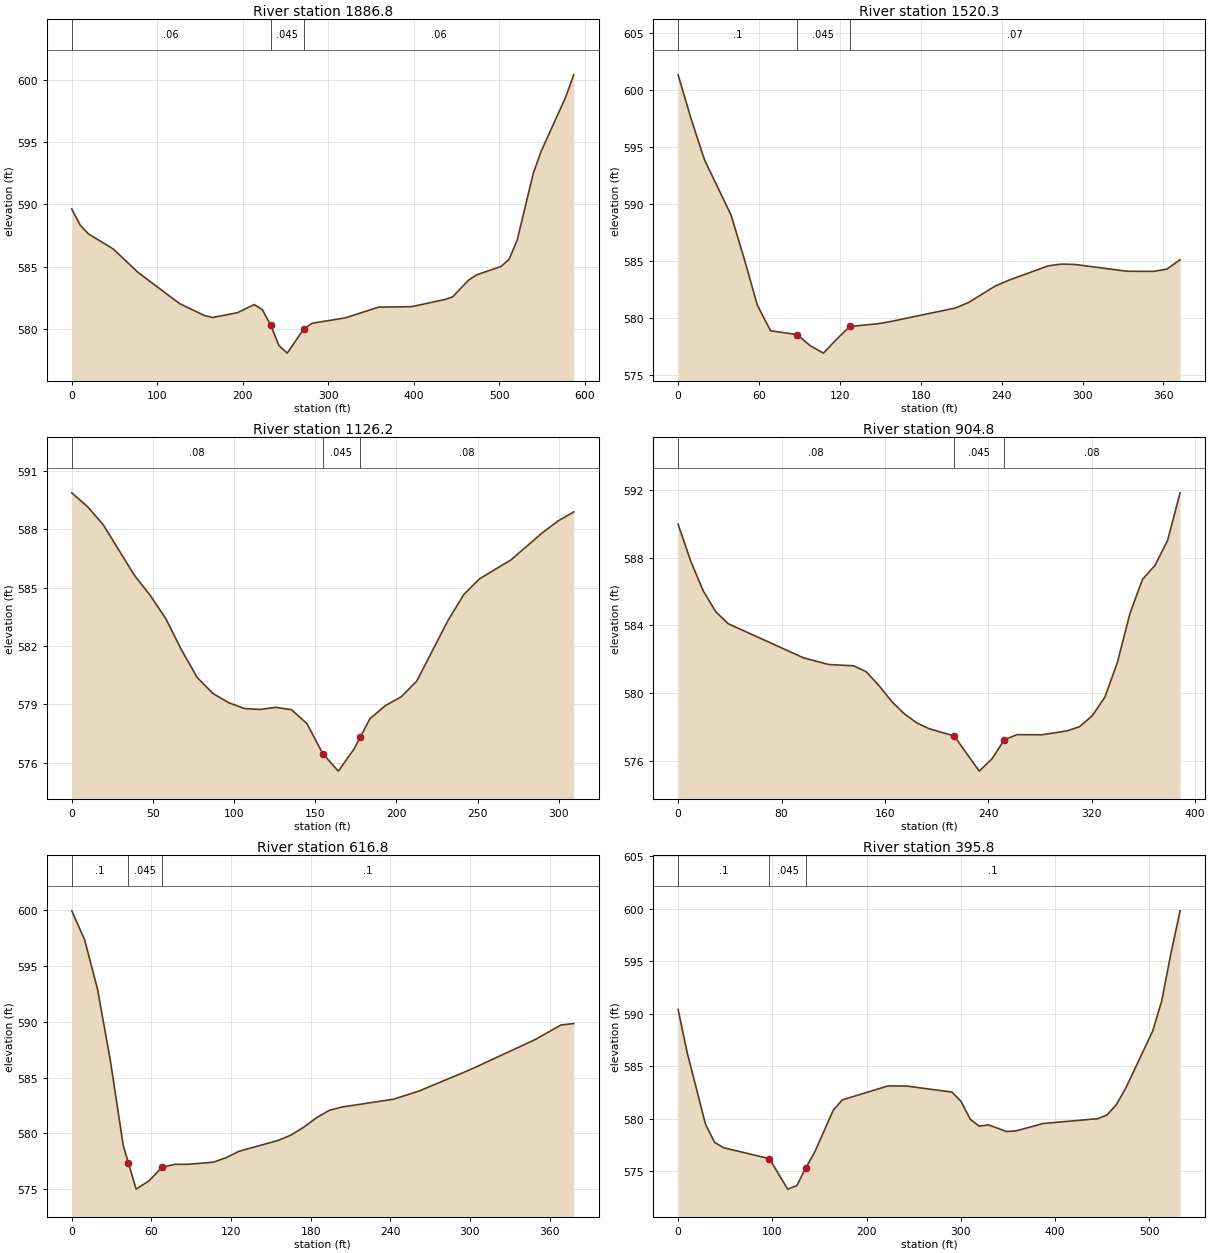
Type RM Length L Ch R = 1 ,1886.8  ,394.7,366.6,336.2
XS GIS Cut Line= 3
     1730990.914      521614.333     1730566.318      521652.517
     1730551.549      521812.282
#Sta/Elev= 30
       0  589.64     9.7  588.35    19.4  587.64    48.4  586.43    77.5  584.54
     126  582.04     155  581.08   164.7  580.92   193.8  581.31   213.2  581.96
   222.8  581.55   232.5  580.31   242.2  578.67   251.9  578.06   271.3  580.01
     281  580.46   319.7  580.89   358.5  581.75   397.2  581.79   435.8  582.36
   445.2  582.58   464.1  583.94   473.5  584.35   501.8  585.02   511.2  585.59
   520.7  587.14   539.6  592.52     549  594.32   577.3   598.6   586.8  600.41
#Mann= 3 , 0 , 0
       0     .06       0   232.5    .045       0   271.3     .06       0
Bank Sta=232.5,271.3
XS Rating Curve= 0 ,0
Exp/Cntr=0.3,0.1

Type RM Length L Ch R = 1 ,1520.3  ,400.8,394,384
XS GIS Cut Line= 2
     1730535.943      521337.327     1730426.521       521693.32
#Sta/Elev= 25
       0  601.34     9.8  597.41    19.6  593.88    39.2  589.06      49  585.23
    58.8  581.13    68.6  578.89    88.2  578.56      98  577.58   107.8  576.93
   117.6  578.15   127.4  579.27     147  579.49   156.8  579.68   205.8  580.89
   215.6  581.38   235.2  582.81     245  583.31   274.4  584.58   284.2  584.74
     294  584.71   333.2  584.11   352.8   584.1   362.6   584.3   372.4  585.12
#Mann= 3 , 0 , 0
       0      .1       0    88.2    .045       0   127.4     .07       0
Bank Sta=88.2,127.4
XS Rating Curve= 0 ,0
Exp/Cntr=0.3,0.1

Type RM Length L Ch R = 1 ,1126.2  ,220.6,221.4,221.6
XS GIS Cut Line= 2
     1730179.078       521286.08     1730184.273      521595.191
#Sta/Elev= 30
       0  589.87     9.7  589.16    19.3  588.24    38.6  585.63    48.3   584.6
      58  583.39    67.6  581.79    77.3  580.37      87  579.55    96.6  579.08
   106.3  578.78   115.9  578.73   125.6  578.84   135.3  578.72   144.9     578
   154.6  576.46   164.2  575.56   173.9   576.7   177.6  577.29   183.6  578.25
   193.2  578.93   202.9  579.38   212.5  580.19   231.9  583.33   241.5  584.64
   251.2  585.45   270.5  586.42   289.8  587.81   299.5  588.42   309.2  588.89
#Mann= 3 , 0 , 0
       0     .08       0   154.6    .045       0   177.6     .08       0
Bank Sta=154.6,177.6
XS Rating Curve= 0 ,0
Exp/Cntr=0.3,0.1

Type RM Length L Ch R = 1 ,904.8   ,295.3,288.1,280.4
XS GIS Cut Line= 2
       1729975.9      521252.207      1729961.12      521640.332
#Sta/Elev= 30
       0  589.96     9.7   587.8    19.4  586.04    29.1  584.81    38.8   584.1
    97.1  582.09   116.5   581.7   135.9  581.62   145.6  581.27   155.4  580.46
   165.1  579.54   174.8  578.81   184.5  578.27   194.2  577.92   213.6  577.49
     233  575.42   242.8  576.14   252.5  577.27   262.2  577.57   281.6  577.56
     301  577.79   310.7  578.04   320.4  578.68   330.2  579.78   339.9  581.82
   349.6   584.7   359.3  586.71     369  587.54   378.7     589   388.4  591.81
#Mann= 3 , 0 , 0
       0     .08       0   213.6    .045       0   252.5     .08       0
Bank Sta=213.6,252.5
XS Rating Curve= 0 ,0
Exp/Cntr=0.3,0.1

Type RM Length L Ch R = 1 ,616.8   ,217.9,220.9,223.5
XS GIS Cut Line= 2
     1729689.359      521372.017     1729798.745      521734.099
#Sta/Elev= 26
       0  599.93     9.7  597.34    19.4  592.92    29.1  586.51    38.8  578.92
    42.6  577.39    48.5  575.02    58.2  575.76    67.9  576.97    77.6  577.24
    87.3  577.24   106.7  577.43   116.4  577.84   126.1  578.41   155.2  579.37
   164.9  579.84   174.6  580.55   184.3   581.4     194  582.07   203.7  582.37
   242.5  583.07   261.9  583.81   300.7  585.74   349.2  588.41   368.6  589.71
   378.2  589.84
#Mann= 3 , 0 , 0
       0      .1       0    42.6    .045       0    67.9      .1       0
Bank Sta=42.6,67.9
XS Rating Curve= 0 ,0
Exp/Cntr=0.3,0.1

Type RM Length L Ch R = 1 ,395.8   ,329.5,320.3,308.9
XS GIS Cut Line= 2
     1729506.147      521429.315     1729600.765      521953.766
#Sta/Elev= 30
       0  590.42     9.7  586.28    29.1  579.48    38.8  577.76    48.4  577.25
    96.9  576.21   116.3  573.31     126  573.64   135.6  575.33   145.3  576.89
   164.7  580.83   174.4  581.81   222.9  583.14   242.2  583.13   290.7  582.55
   300.4  581.66   310.1  579.97   319.8   579.3   329.4  579.43   348.8   578.8
   358.5  578.85   387.6  579.56   445.7  580.02   455.4  580.38   465.1  581.34
   474.8  582.85   503.8  588.36   513.5  591.26   523.2  595.77   532.9  599.81
#Mann= 3 , 0 , 0
       0      .1       0    96.9    .045       0   135.6      .1       0
Bank Sta=96.9,135.6
XS Rating Curve= 0 ,0
Exp/Cntr=0.3,0.1

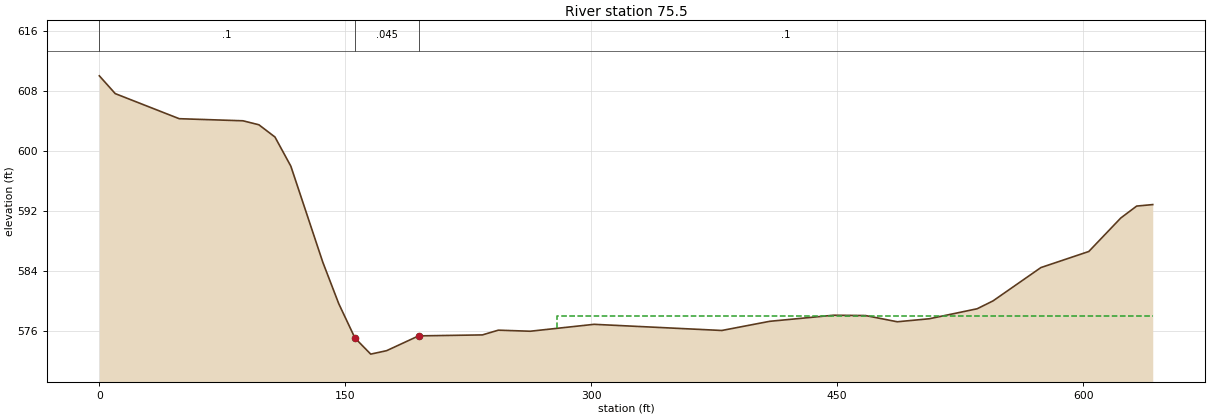
Type RM Length L Ch R = 1 ,75.5    ,83.9,75.5,67.1
XS GIS Cut Line= 2
     1729156.224      521470.107     1729502.645      522011.069
#Sta/Elev= 30
       0  609.98     9.7  607.61    48.7  604.27    87.6  603.99    97.3  603.46
   107.1  601.83   116.8  597.94   136.3  585.14     146  579.63   155.9  575.05
   165.5  572.91   175.2  573.37   194.7  575.34   233.6  575.47   243.3   576.1
   262.8  575.96   301.7  576.88   379.6  576.06   408.8  577.28   447.7  578.09
   467.2  578.05   486.6  577.22   506.1  577.62   535.3  578.95     545     580
   574.2  584.44   603.4  586.58   622.9  591.04   632.6  592.63   642.4  592.83
#Mann= 3 , 0 , 0
       0      .1       0   155.9    .045       0   194.7      .1       0
#XS Ineff= 2 , 0
                          279.01          578.03
Permanent Ineff=
       F       F
Bank Sta=155.9,194.7
XS Rating Curve= 0 ,0
Exp/Cntr=0.3,0.1

Chan Stop Cuts=-1
Use User Specified Reach Order=0
Composite Channel Slope=5